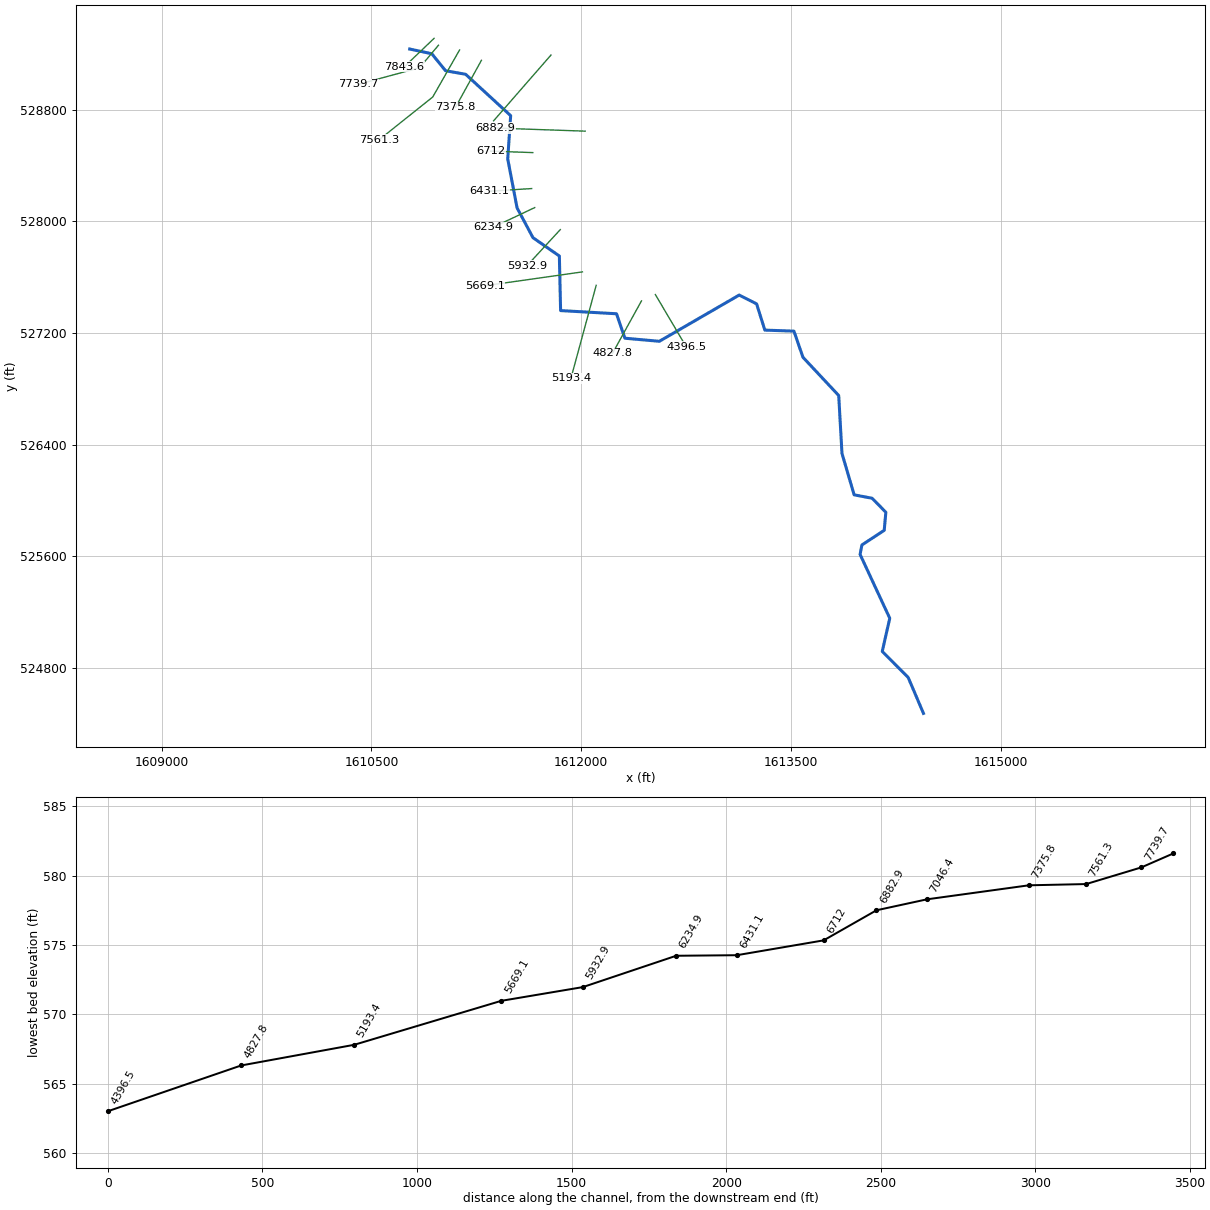
--- LCabellCr.prj (project) ---

Proj Title=LCabellCr
Current Plan=p01
Default Exp/Contr=0,0
English Units
Geom File=g01
Flow File=f01
Plan File=p01
BEGIN DESCRIPTION:
END DESCRIPTION:
DSS Export Rating Curves= 0
DSS Export Rating Curve Sorted= 0
DSS Export Volume Flow Curves= 0
DXF OffsetX= 0
DXF OffsetY= 0
DXF ScaleX= 0
DXF ScaleY= 0

--- LCabellCr.p01 (plan) ---

Plan Title=Floodplain
Program Version=4.00
Geom File=g01
Flow File=f01
K Sum by GR=0
Std Step Tol=0.01
Critical Tol=0.01
Num of Std Step Trials=20
Max Error Tol=0.3
Flow Tol Ratio=0.001
Split Flow NTrial=30
Split Flow Tol=0.02
Split Flow Ratio=0.02
Log Output Level=0
Friction Slope Method=1
Unsteady Friction Slope Method=2
Unsteady Bridges Friction Slope Method=1
Global Log Level=0
CheckData=False
Run HTab=0
Run UNet=0
Run PostProcess=0
UNET Theta=0
UNET Theta Warmup=0
UNET ZTol=0
UNET ZSATol=0
UNET MxIter=0
UNET MaxInSteps=0
UNET DtIC=0
UNET DtMin=0
UNET MaxCRTS=0
UNET WFStab=0
UNET SFStab=0
UNET WFX=0
UNET SFX=0
UNET DSS MLevel=0
UNET DZMax Abort=0
UNET Convert EG Bridges=0
UNET Use Existing IB Tables=0
UNET Froude Limit=0
UNET Froude Power=0
Write IC File=0
Echo Input=False
Echo Output=False
Write Detailed=0

--- LCabellCr.f01 (steady flow) ---

Flow Title=NFF Regression Equation
Program Version=4.10
Number of Profiles= 1
Profile Names=P100yr
River Rch & RM=LCabellCr,Main            ,7843.6
     760
River Rch & RM=LCabellCr,Main            ,7739.7
     762
River Rch & RM=LCabellCr,Main            ,7375.8
    1003
River Rch & RM=LCabellCr,Main            ,7046.4
    1005
River Rch & RM=LCabellCr,Main            ,6882.9
    1122
River Rch & RM=LCabellCr,Main            ,6431.1
    1125
River Rch & RM=LCabellCr,Main            ,5932.9
    1137
River Rch & RM=LCabellCr,Main            ,5669.1
    1140
River Rch & RM=LCabellCr,Main            ,4396.5
    1193
Boundary for River Rch & Prof#=LCabellCr,Main            , 1
Up Type= 0
Dn Type= 3
Dn Slope=0.00765
DSS Import GetInterval= 0
DSS Import GetPeak= 0
DSS Import FillOption= 0

--- LCabellCr.g01 (geometry) ---

Geom Title=USGS 10m DEM
Program Version=4.10

River Reach=LCabellCr       ,Main
Reach XY= 30
     1610773.643      529235.542     1610931.175       529201.96
     1611029.888      529080.073     1611173.338      529054.638
     1611495.378      528758.199      1611474.48      528447.979
     1611541.281      528096.679       1611655.2      527883.156
     1611843.672      527751.941     1611852.619      527360.681
     1612252.229      527338.016     1612312.469      527162.665
     1612558.796      527140.597     1613129.742      527471.961
     1613254.215       527408.97     1613313.394      527220.789
      1613521.44      527213.362     1613585.854      527026.081
     1613841.671      526751.973     1613864.985      526336.604
     1613951.981      526039.891     1614080.585      526015.369
     1614178.709      525914.926     1614167.081      525785.564
     1614007.533      525680.528     1613994.411      525613.131
     1614206.742       525155.07     1614153.063      524917.689
     1614338.553      524730.409     1614447.878      524473.335

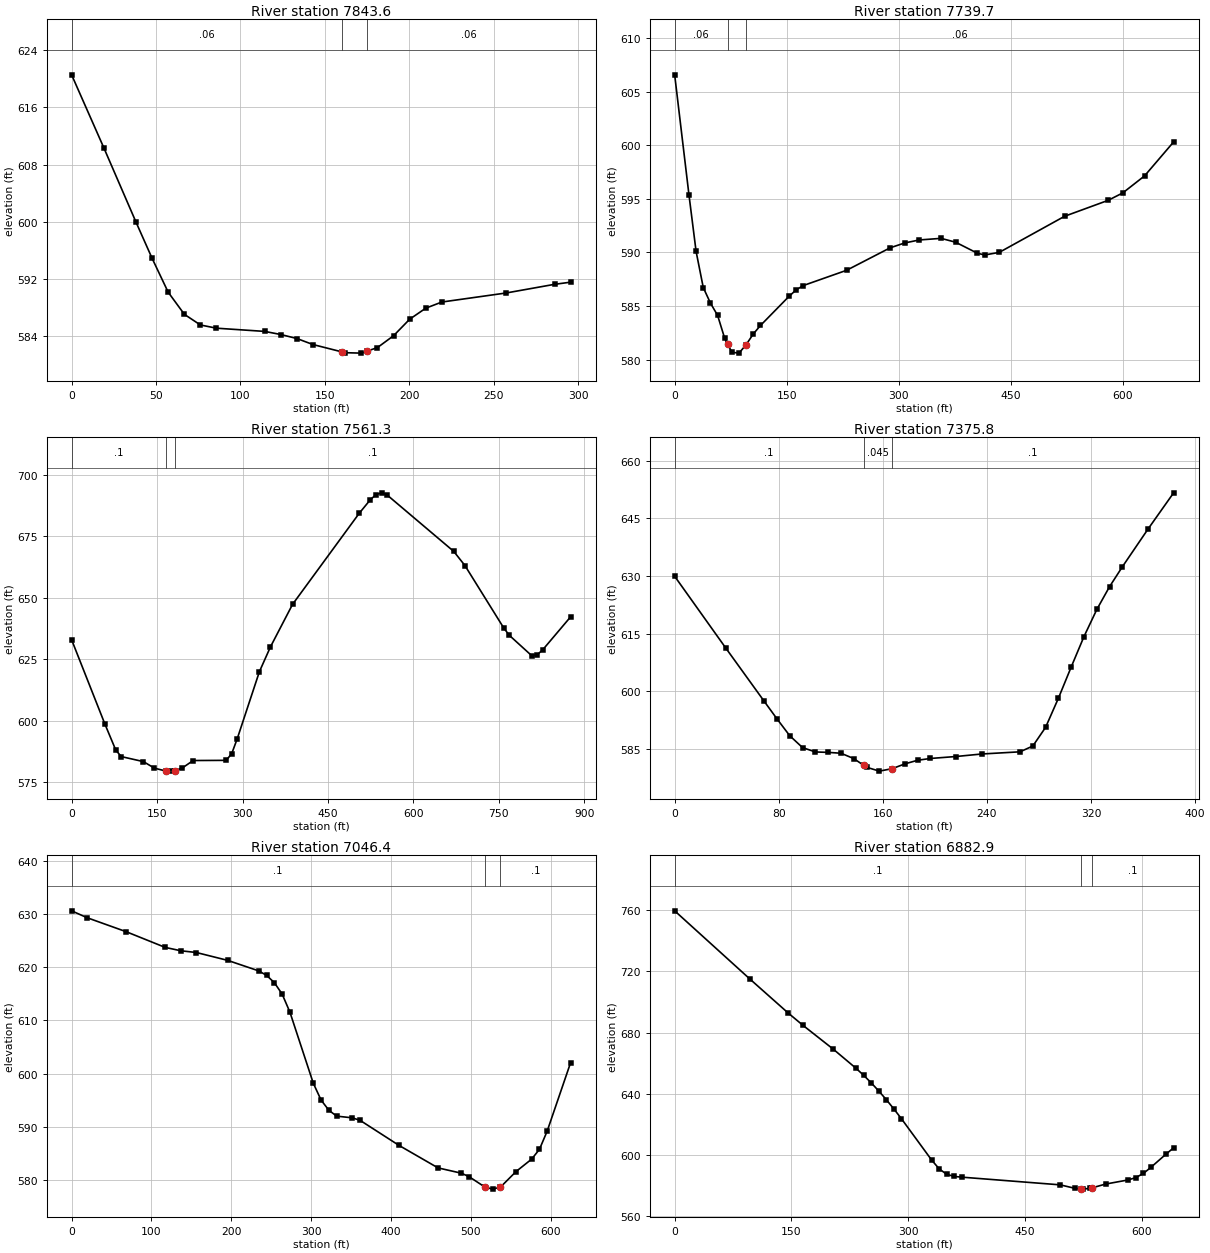
Type RM Length L Ch R = 1 ,7843.6  ,90.8,103.8,108.1
XS GIS Cut Line= 2
     1610947.782      529312.389     1610734.241      529107.962
#Sta/Elev= 24
       0  620.56    19.1  610.34    38.1  599.97    47.7  594.87    57.2  590.14
    66.8  587.04    76.3  585.55    85.8   585.1   114.4  584.65     124  584.21
   133.5  583.65     143  582.81   160.2  581.78   162.1  581.67   171.6  581.61
   175.2   581.9   181.2  582.39   190.7  584.04   200.3  586.36   209.8   587.9
   219.3  588.76   257.5  590.03   286.1  591.24   295.6  591.54
#Mann= 3 , 0 , 0
       0     .06       0   160.2    .045       0   175.2     .06       0
Bank Sta=160.2,175.2
XS Rating Curve= 0 ,0
Exp/Cntr=0.3,0.1

Type RM Length L Ch R = 1 ,7739.7  ,174.2,178.4,183.2
XS GIS Cut Line= 3
     1610979.032       529262.91     1610843.616      529101.452
     1610402.209       528981.66
#Sta/Elev= 30
       0  606.57    19.2  595.34    28.7  590.09    38.3  586.72    47.9  585.27
    57.5  584.12      67  581.98    71.2  581.41    76.6  580.68    86.2   580.6
    95.8   581.4   105.4   582.4   114.9  583.18   153.3  585.91   162.8  586.51
   172.4  586.91   230.2  588.33   288.6  590.43     308  590.88   327.5  591.16
   356.7  591.31   376.2  590.95   405.4  589.92   415.1  589.76   434.6     590
   522.1  593.37   580.5  594.86     600  595.55   629.2  597.14   668.1  600.31
#Mann= 3 , 0 , 0
       0     .06       0    71.2    .045       0    95.8     .06       0
Bank Sta=71.2,95.8
XS Rating Curve= 0 ,0
Exp/Cntr=0.3,0.1

Type RM Length L Ch R = 1 ,7561.3  ,183.3,185.5,185.5
XS GIS Cut Line= 3
     1611130.074      529229.056     1610938.216      528892.074
     1610557.157      528587.129
#Sta/Elev= 30
       0  632.91    58.2   598.7    77.6  587.92    87.2  585.32     126  583.28
   145.4   580.6   165.7  579.43   174.5   579.4   180.7  579.61   193.9  580.62
   213.3  583.72   271.4  583.79   281.1  586.58   290.8  592.66   329.6  619.91
     349  630.01   387.8  647.33   504.9  684.45   524.4  689.97   534.2  692.02
     544  692.76   553.7  691.89   670.8  668.89   690.4  663.13   758.7  637.63
   768.4  634.69   807.5  626.44   817.3  626.82     827  628.85   875.8  642.23
#Mann= 3 , 0 , 0
       0      .1       0   165.7    .045       0   180.7      .1       0
Bank Sta=165.7,180.7
XS Rating Curve= 0 ,0
Exp/Cntr=0.3,0.1

Type RM Length L Ch R = 1 ,7375.8  ,334,329.3,324.5
XS GIS Cut Line= 2
     1611286.324      529154.837     1611101.428        528818.9
#Sta/Elev= 30
       0  629.93    39.3  611.28    68.8  597.46    78.7  592.86    88.5  588.49
    98.3  585.42   108.2  584.29     118  584.18   127.8  583.96   137.6  582.58
   145.3  580.82   147.5  580.32   157.3  579.31   167.2  579.95     177   581.2
   186.8  582.14   196.6   582.6   216.3  583.11     236  583.76   265.5  584.33
   275.3  585.84   285.1  590.69     295   598.3   304.8  606.38   314.6  614.27
   324.5  621.33   334.3  627.26   344.1   632.4   363.8  642.19   383.5  651.61
#Mann= 3 , 0 , 0
       0      .1       0   145.3    .045       0   167.2      .1       0
Bank Sta=145.3,167.2
XS Rating Curve= 0 ,0
Exp/Cntr=0.3,0.1

Type RM Length L Ch R = 1 ,7046.4  ,183.3,163.5,142.8
XS GIS Cut Line= 2
      1611783.72      529192.598     1611373.564      528721.244
#Sta/Elev= 30
       0  630.57    19.5  629.27    68.3  626.65   117.2   623.7   136.7  623.07
   156.2  622.74   195.3  621.27   234.3  619.29   244.1  618.45   253.8  617.09
   263.6  614.94   273.4  611.52   302.6   598.2   312.4  595.02   322.2   593.1
   331.9  592.01   351.5  591.69   361.2  591.22     410  586.51   458.8  582.29
   488.1  581.29   497.9  580.62   517.4   578.7   527.2   578.3     537  578.68
   556.5   581.6     576  583.93   585.8  585.77   595.5   589.2   624.8  602.04
#Mann= 3 , 0 , 0
       0      .1       0   517.4    .045       0     537      .1       0
Bank Sta=517.4,537
XS Rating Curve= 0 ,0
Exp/Cntr=0.3,0.1

Type RM Length L Ch R = 1 ,6882.9  ,170.3,171,170.2
XS GIS Cut Line= 2
     1612028.512      528647.025     1611387.887       528669.16
#Sta/Elev= 30
       0   759.7    97.1  714.84   145.7  692.86   165.1  684.63     204  669.03
   233.1  656.56   242.8  652.03   252.5   647.1   262.2  641.76   271.9  636.07
   281.6  630.01   291.4  623.55   330.2   596.5   339.9  590.74   349.6  587.17
   359.4  585.81   369.1  585.34   495.3  580.31   514.8  577.96   521.7  577.64
   524.5  577.51   534.2  578.07   536.7  578.42   553.6  580.82   582.7  583.54
   592.4  585.05   602.2  587.81   611.9  591.81   631.3  600.46     641  604.55
#Mann= 3 , 0 , 0
       0      .1       0   521.7    .045       0   536.7      .1       0
Bank Sta=521.7,536.7
XS Rating Curve= 0 ,0
Exp/Cntr=0.3,0.1

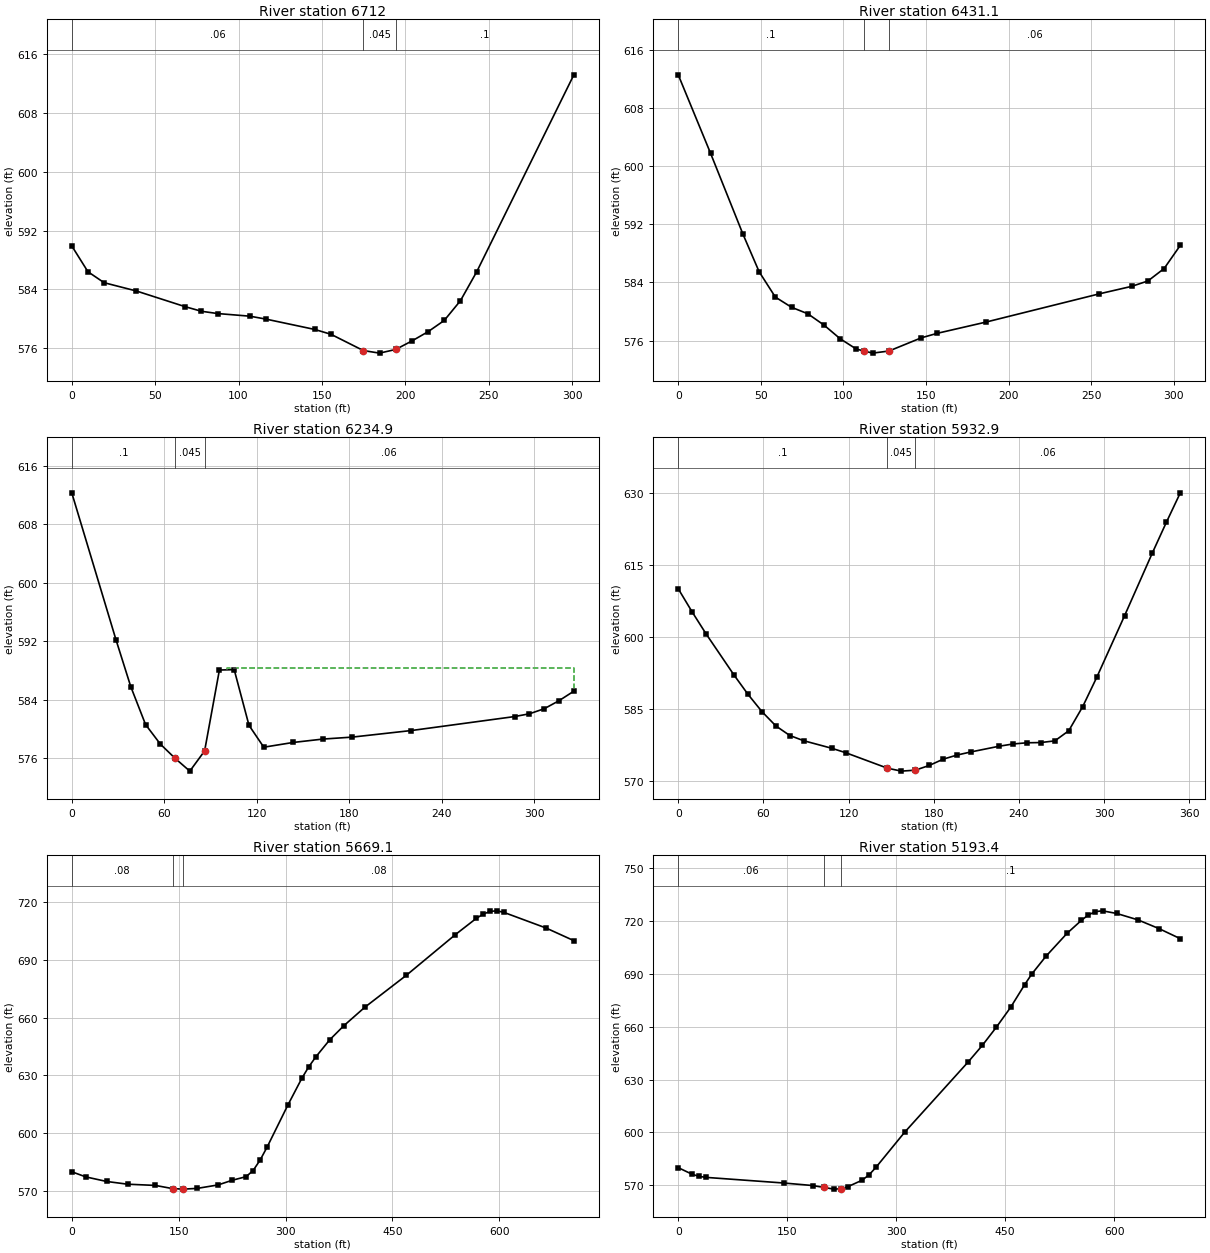
Type RM Length L Ch R = 1 ,6712    ,278,280.9,283.9
XS GIS Cut Line= 2
     1611653.563      528493.228      1611352.73      528503.796
#Sta/Elev= 20
       0  589.91     9.7   586.4    19.4  584.91    38.8  583.78      68  581.65
    77.7  581.03    87.4  580.72   106.8  580.36   116.5  579.96   145.6  578.56
   155.4   577.9   174.8  575.69   184.5  575.34   194.2  575.84   203.9  576.99
   213.6  578.25   223.3  579.78     233  582.46   242.8  586.41     301  613.16
#Mann= 3 , 0 , 0
       0     .06       0   174.8    .045       0   194.2      .1       0
Bank Sta=174.8,194.2
XS Rating Curve= 0 ,0
Exp/Cntr=0.3,0.1

Type RM Length L Ch R = 1 ,6431.1  ,187.1,196.1,204.6
XS GIS Cut Line= 2
     1611645.699      528235.566     1611342.314      528216.035
#Sta/Elev= 21
       0  612.56    19.6  601.75    39.2  590.63      49  585.46    58.8  581.98
    68.6  580.58    78.5  579.68    88.3  578.12    98.1  576.24   107.9  574.82
   112.6  574.56   117.7  574.27   127.6  574.56   147.1  576.37   156.9     577
   186.3  578.54     255  582.43   274.6  583.46   284.4   584.2   294.2  585.91
     304   589.1
#Mann= 3 , 0 , 0
       0      .1       0   112.6    .045       0   127.6     .06       0
Bank Sta=112.6,127.6
XS Rating Curve= 0 ,0
Exp/Cntr=0.3,0.1

Type RM Length L Ch R = 1 ,6234.9  ,292.6,302,310.1
XS GIS Cut Line= 2
     1611667.452      528099.131     1611373.181      527959.374
#Sta/Elev= 21
       0  612.27    28.7  592.18    38.3  585.77    47.9  580.59    57.5  577.92
    67.1  575.97    76.6  574.23    86.2  576.99    95.8  588.05   105.4   588.1
     115  580.49   124.6   577.5   143.7  578.15   162.9  578.61     182  578.88
   220.4  579.78   287.4  581.69     297  582.07   306.6  582.76   316.2  583.86
   325.8  585.16
#Mann= 3 , 0 , 0
       0      .1       0    67.1    .045       0    86.2     .06       0
#XS Ineff= 2 , 0
                          100.56          588.28
Permanent Ineff=
       F       F
Bank Sta=67.1,86.2
XS Rating Curve= 0 ,0
Exp/Cntr=0.3,0.1

Type RM Length L Ch R = 1 ,5932.9  ,279,263.8,247.7
XS GIS Cut Line= 2
     1611850.353      527941.206     1611610.727      527681.043
#Sta/Elev= 30
       0     610     9.8  605.17    19.6   600.6    39.3  592.01    49.1     588
      59  584.37    68.8  581.39    78.6   579.4    88.4  578.31   108.1  576.74
   117.9  575.82   147.4  572.58   157.2  571.97     167  572.17   176.8  573.15
   186.7  574.47   196.5  575.33   206.3  575.98     226  577.16   235.8  577.63
   245.6  577.88   255.4  577.93   265.3  578.28   275.1  580.39   284.9   585.4
   294.8  591.51   314.4  604.36     334  617.47   343.9  623.88   353.7  630.01
#Mann= 3 , 0 , 0
       0      .1       0   147.4    .045       0     167     .06       0
Bank Sta=147.4,167
XS Rating Curve= 0 ,0
Exp/Cntr=0.3,0.1

Type RM Length L Ch R = 1 ,5669.1  ,447.7,475.8,501.1
XS GIS Cut Line= 2
     1612008.685      527638.088     1611310.995      527538.791
#Sta/Elev= 30
       0     580    19.6  577.34    48.9  574.96    78.3  573.54   117.4   572.9
   141.6  571.24   156.6  570.98   176.2  571.37   205.5  573.17   225.1  575.58
   244.7  577.45   254.5  580.63   264.3  586.04   274.1  592.75   303.4   614.7
     323   628.6   332.8  634.59   342.6  639.69   362.2  648.58   381.7  655.78
   411.1  665.36   469.8  682.08   538.3  703.11   567.7  711.56   577.5  713.79
   587.3  715.22   597.1   715.5   606.8  714.65   665.6  706.59   704.7  700.01
#Mann= 3 , 0 , 0
       0     .08       0   141.6    .045       0   156.6     .08       0
Bank Sta=141.6,156.6
XS Rating Curve= 0 ,0
Exp/Cntr=0.3,0.1

Type RM Length L Ch R = 1 ,5193.4  ,366.2,365.6,361.5
XS GIS Cut Line= 2
      1612107.11      527541.844     1611926.403      526874.673
#Sta/Elev= 30
       0     580    19.5  576.18    29.2  575.01    38.9  574.46     146  571.26
     185  569.85   200.9  568.75   214.2  567.81   223.9  568.03   233.6  569.22
   253.1  572.87   262.8  575.94   272.6  580.38   311.5  600.02   399.2  640.04
   418.6   649.4   438.1  659.83   457.6  671.02     477  683.95   486.8  689.98
   506.2     700   535.4  713.09   554.9  720.37   564.6  723.49   574.4  725.36
   584.1  725.82   603.6  724.32   632.8   720.7     662   715.7   691.2     710
#Mann= 3 , 0 , 0
       0     .06       0   200.9    .045       0   223.9      .1       0
Bank Sta=200.9,223.9
XS Rating Curve= 0 ,0
Exp/Cntr=0.3,0.1

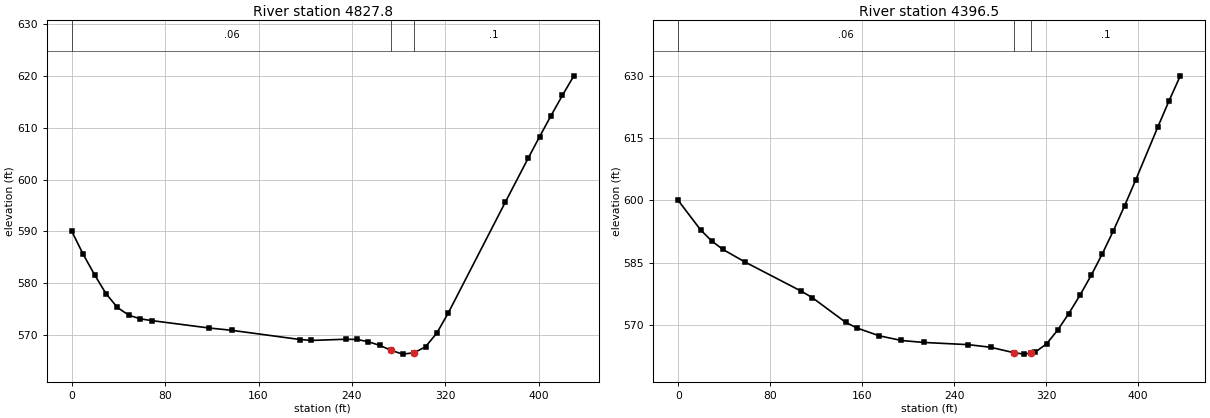
Type RM Length L Ch R = 1 ,4827.8  ,411.5,431.2,454.2
XS GIS Cut Line= 2
     1612431.056      527430.253     1612223.388      527053.549
#Sta/Elev= 28
       0  590.01     9.8  585.57    19.6   581.6    29.3     578    39.1  575.32
    48.9  573.83    58.7  573.13    68.4  572.79   117.3  571.37   136.9  570.92
   195.5  569.14   205.3  568.96   234.6  569.19   244.4  569.15   254.2   568.7
     264     568   273.9  567.03   283.5  566.32   293.3  566.58   303.1  567.74
   312.8  570.38   322.6  574.26   371.5  595.64     391  604.08   400.8  608.24
   410.6   612.3   420.4  616.23   430.2     620
#Mann= 3 , 0 , 0
       0     .06       0   273.9    .045       0   293.3      .1       0
Bank Sta=273.9,293.3
XS Rating Curve= 0 ,0
Exp/Cntr=0.3,0.1

Type RM Length L Ch R = 1 ,4396.5  ,4438.1,4396.5,4346.4
XS GIS Cut Line= 2
     1612530.338      527475.573     1612752.203      527099.263
#Sta/Elev= 30
       0     600    19.4  592.93    29.1  590.26    38.8  588.22    58.2  585.17
   106.8   578.2   116.5  576.64   145.6  570.68   155.3  569.33   174.7  567.44
   194.2   566.3   213.6  565.83   252.4   565.3   271.8  564.67   291.7  563.38
   300.9  563.02   306.7  563.31   310.6   563.5   320.4  565.49   330.1   568.8
   339.8  572.79   349.5  577.19   359.2  581.95   368.9  587.13   378.6  592.73
   388.3   598.7     398  604.93   417.4  617.79   427.1  624.05   436.8  629.99
#Mann= 3 , 0 , 0
       0     .06       0   291.7    .045       0   306.7      .1       0
Bank Sta=291.7,306.7
XS Rating Curve= 0 ,0
Exp/Cntr=0.3,0.1

Chan Stop Cuts=-1
Use User Specified Reach Order=0
Composite Channel Slope=5